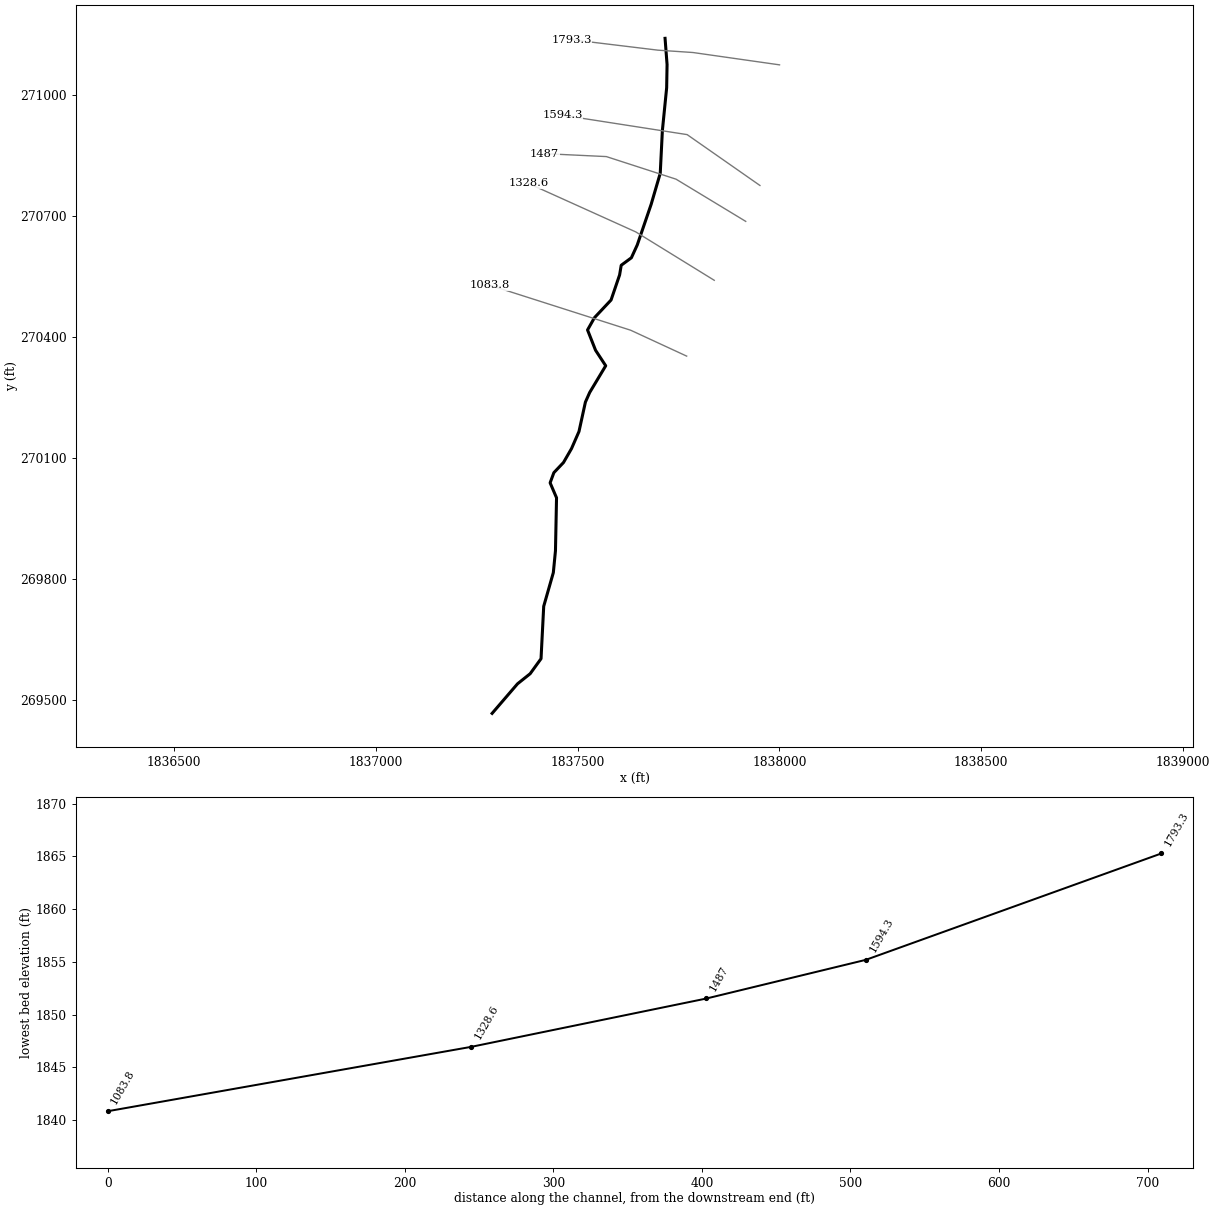
--- UpperBigBr.prj (project) ---

Proj Title=UpperBigBr
Current Plan=p01
Default Exp/Contr=0,0
English Units
Geom File=g01
Flow File=f01
Plan File=p01
BEGIN DESCRIPTION:
END DESCRIPTION:
DSS Export Rating Curves= 0
DSS Export Rating Curve Sorted= 0
DSS Export Volume Flow Curves= 0
DXF OffsetX= 0
DXF OffsetY= 0
DXF ScaleX= 0
DXF ScaleY= 0

--- UpperBigBr.p01 (plan) ---

Plan Title=Floodplain
Program Version=4.00
Geom File=g01
Flow File=f01
K Sum by GR=0
Std Step Tol=0.01
Critical Tol=0.01
Num of Std Step Trials=20
Max Error Tol=0.3
Flow Tol Ratio=0.001
Split Flow NTrial=30
Split Flow Tol=0.02
Split Flow Ratio=0.02
Log Output Level=0
Friction Slope Method=1
Unsteady Friction Slope Method=2
Unsteady Bridges Friction Slope Method=1
Global Log Level=0
CheckData=False
Run HTab=0
Run UNet=0
Run PostProcess=0
UNET Theta=0
UNET Theta Warmup=0
UNET ZTol=0
UNET ZSATol=0
UNET MxIter=0
UNET MaxInSteps=0
UNET DtIC=0
UNET DtMin=0
UNET MaxCRTS=0
UNET WFStab=0
UNET SFStab=0
UNET WFX=0
UNET SFX=0
UNET DSS MLevel=0
UNET DZMax Abort=0
UNET Convert EG Bridges=0
UNET Use Existing IB Tables=0
UNET Froude Limit=0
UNET Froude Power=0
Write IC File=0
Echo Input=False
Echo Output=False
Write Detailed=0

--- UpperBigBr.f01 (steady flow) ---

Flow Title=NFF Regression Equation
Program Version=4.00
Number of Profiles= 1
Profile Names=P100yr
River Rch & RM=UpperBigBr,Main            ,1793.3
 364.291
Boundary for River Rch & Prof#=UpperBigBr,Main            , 1
Up Type= 0
Dn Type= 3
Dn Slope=0.028945
DSS Import GetInterval= 0
DSS Import GetPeak= 0
DSS Import FillOption= 0

--- UpperBigBr.g01 (geometry) ---

Geom Title=USGS 10m DEM
Program Version=4.00

River Reach=UpperBigBr      ,Main
Reach XY= 30
      1837716.74      271139.369     1837721.722      271074.415
     1837720.687      271016.858     1837710.095      270910.936
     1837704.799      270805.015     1837682.291      270728.221
     1837647.866      270627.596     1837633.302       270595.82
     1837608.146      270577.283     1837604.174      270553.451
     1837582.989      270491.222     1837541.945      270447.529
     1837524.732      270417.077     1837544.593      270366.764
     1837569.749      270328.367     1837530.029      270262.166
     1837519.436      270238.334     1837503.548      270165.513
     1837485.012      270123.144     1837465.151      270088.719
     1837441.319      270063.563     1837432.051      270038.407
     1837447.939      270001.334     1837445.291      269870.256
     1837439.995      269815.971     1837416.163      269732.558
     1837409.543      269602.804     1837382.584      269565.575
     1837351.286      269540.575     1837288.355      269467.366

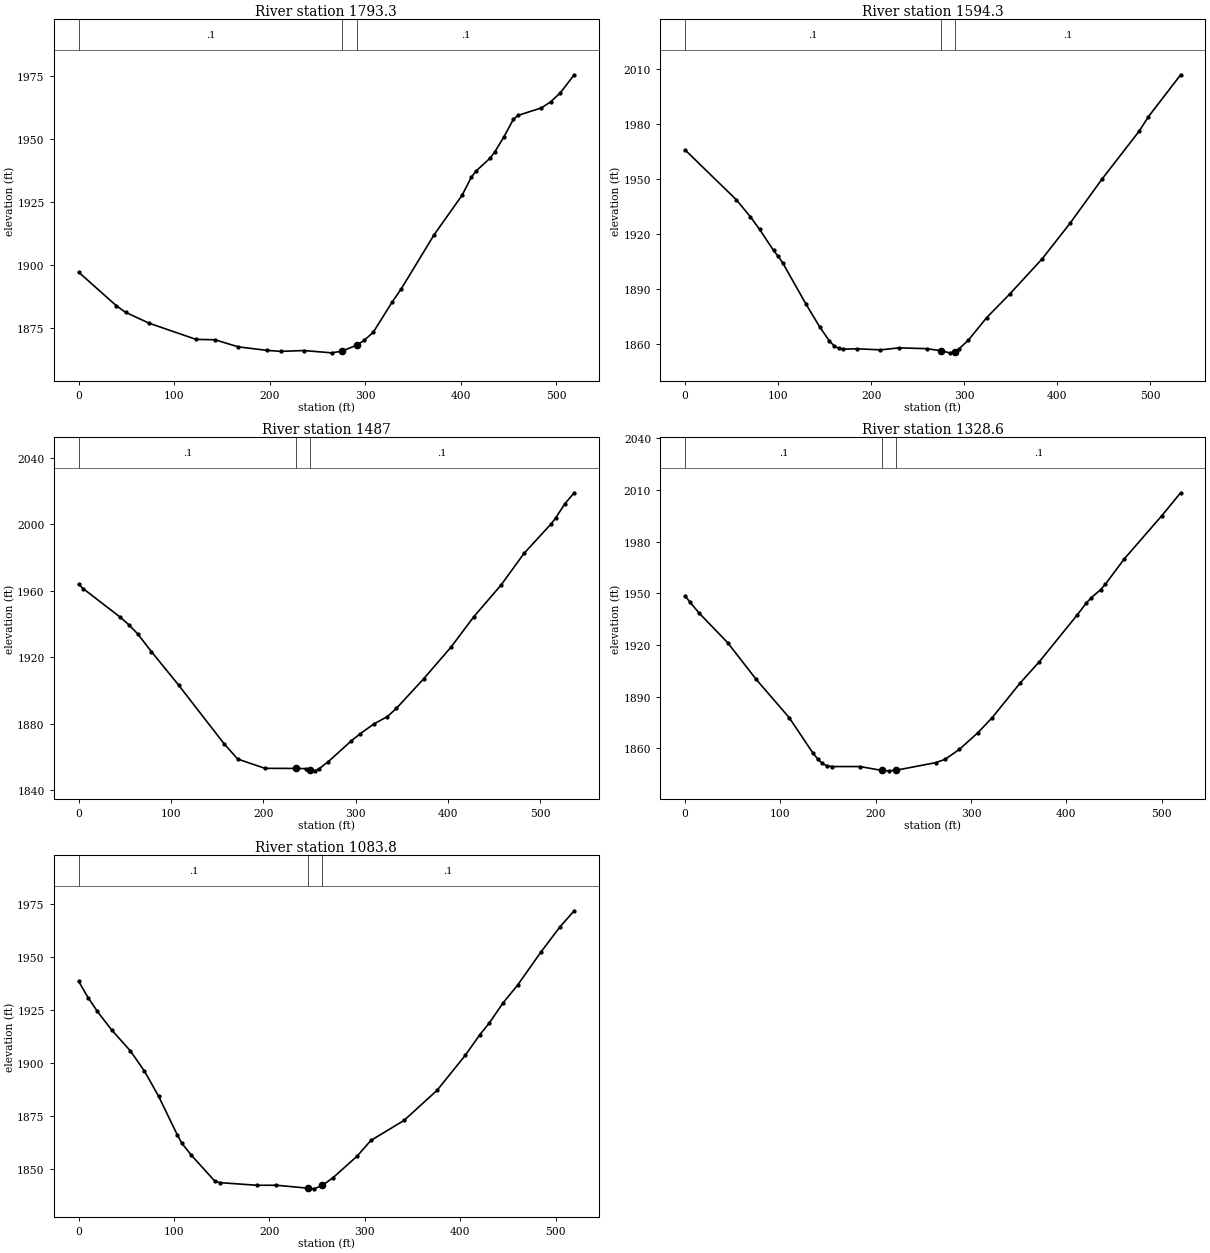
Type RM Length L Ch R = 1 ,1793.3  ,201,199,197.2
XS GIS Cut Line= 4
     1838000.249      271073.684     1837785.874      271104.239
     1837698.876      271110.095     1837485.303      271135.976
#Sta/Elev= 30
       0  1897.3    39.4 1884.02    49.2 1881.36    73.8 1877.05     123 1870.63
   142.7 1870.48   167.3 1867.66   196.9 1866.28   211.6 1865.87   235.9  1866.2
     265 1865.29     276 1865.99     291  1868.3   298.9  1870.2   308.6 1873.51
   328.2 1885.38     338  1890.8   372.2 1912.13   401.5  1927.8   411.3 1935.06
   416.2 1937.45   430.9 1942.57   435.8 1945.03   445.5 1951.13   455.3 1958.01
   460.2 1959.54   484.6 1962.49   494.4 1964.94   504.2 1968.38   518.9 1975.64
#Mann= 3 , 0 , 0
       0      .1       0     276    .045       0     291      .1       0
Bank Sta=276,291
XS Rating Curve= 0 ,0
Exp/Cntr=0.3,0.1

Type RM Length L Ch R = 1 ,1594.3  ,110.9,107.3,103.7
XS GIS Cut Line= 3
     1837951.741      270774.927     1837771.442      270900.889
     1837462.683      270948.923
#Sta/Elev= 30
       0 1965.95      55 1938.77      70 1929.54      80  1922.6      95 1911.09
     100 1907.91     105 1904.15     130  1881.7     145 1869.03     155  1861.7
     160 1859.08     165 1857.61     170 1857.19     185  1857.4   209.9 1856.82
   229.9  1857.9   259.6 1857.47   274.5 1856.37   284.4 1855.19   289.5  1855.7
   294.3  1857.4   304.3  1862.1   324.1 1874.46   348.9 1887.34   383.6 1906.48
   413.4  1925.8   448.1 1950.14   487.8 1976.15   497.7 1984.03   532.4 2006.96
#Mann= 3 , 0 , 0
       0      .1       0   274.5    .045       0   289.5      .1       0
Bank Sta=274.5,289.5
XS Rating Curve= 0 ,0
Exp/Cntr=0.3,0.1

Type RM Length L Ch R = 1 ,1487    ,163.9,158.4,154.2
XS GIS Cut Line= 4
     1837916.512      270686.011     1837743.886       270790.56
     1837571.261      270846.481     1837418.086      270853.775
#Sta/Elev= 30
       0 1963.74     4.9 1961.18    44.3 1944.32    54.2 1939.53      64 1933.93
    78.8 1923.27   108.3 1903.11   157.5 1867.82   172.3  1858.6   201.8 1853.03
   235.9 1852.97     246 1852.84   250.9 1851.96   255.8 1851.52   260.7 1852.92
   270.5 1857.12     295 1869.43   304.8  1873.8   319.5 1879.66   334.2 1884.14
     344 1889.05   373.5 1906.85   403.1 1925.87   427.8 1944.19   457.5 1963.38
   482.2 1982.33   511.9 2000.29   516.8 2003.93   526.7 2012.38   536.6 2018.86
#Mann= 3 , 0 , 0
       0      .1       0   235.9    .045       0   250.9      .1       0
Bank Sta=235.9,250.9
XS Rating Curve= 0 ,0
Exp/Cntr=0.3,0.1

Type RM Length L Ch R = 1 ,1328.6  ,238.2,244.7,249.7
XS GIS Cut Line= 3
     1837838.562       270540.07      1837644.26      270659.869
     1837378.604      270779.836
#Sta/Elev= 30
       0 1948.61       5 1944.89    14.9 1938.41    44.7 1921.29    74.4 1900.14
   109.2  1877.8     134 1857.34   138.9 1853.92   143.9 1851.26   148.9 1849.77
   153.8 1849.42   183.6 1849.42   206.6 1847.13   213.4 1846.93   221.6  1847.3
   262.8 1851.68   272.7 1853.61   287.6 1859.35   307.3 1869.16   322.1  1877.8
   351.8 1898.13   371.5 1910.23   411.1 1937.29   420.9 1944.37   425.9 1947.31
   435.8  1952.1   440.7 1955.15   460.5 1969.86     500 1995.02   519.8 2008.35
#Mann= 3 , 0 , 0
       0      .1       0   206.6    .045       0   221.6      .1       0
Bank Sta=206.6,221.6
XS Rating Curve= 0 ,0
Exp/Cntr=0.3,0.1

Type RM Length L Ch R = 1 ,1083.8  ,1094.1,1083.8,1073.1
XS GIS Cut Line= 3
     1837770.256      270352.258     1837631.567      270416.387
     1837282.231       270527.99
#Sta/Elev= 30
       0 1938.46     9.9 1930.78    19.7 1924.26    34.5 1915.64    54.2 1905.74
      69 1896.21    83.8 1884.41   103.5 1866.14   108.4 1862.17   118.3 1856.57
   142.9 1844.38   147.9 1843.74   187.5 1842.48   207.3 1842.52   240.6 1841.12
     247 1840.82   255.6 1842.47   266.8  1846.1   291.6 1856.06   306.4  1863.6
   341.1 1872.98   375.8  1887.2   405.5 1903.73   420.4 1913.23   430.3 1918.71
   445.2 1928.45   460.1  1936.6   484.8 1952.33   504.7 1964.12   519.5 1971.64
#Mann= 3 , 0 , 0
       0      .1       0   240.6    .045       0   255.6      .1       0
Bank Sta=240.6,255.6
XS Rating Curve= 0 ,0
Exp/Cntr=0.3,0.1

Chan Stop Cuts=-1
Use User Specified Reach Order=0